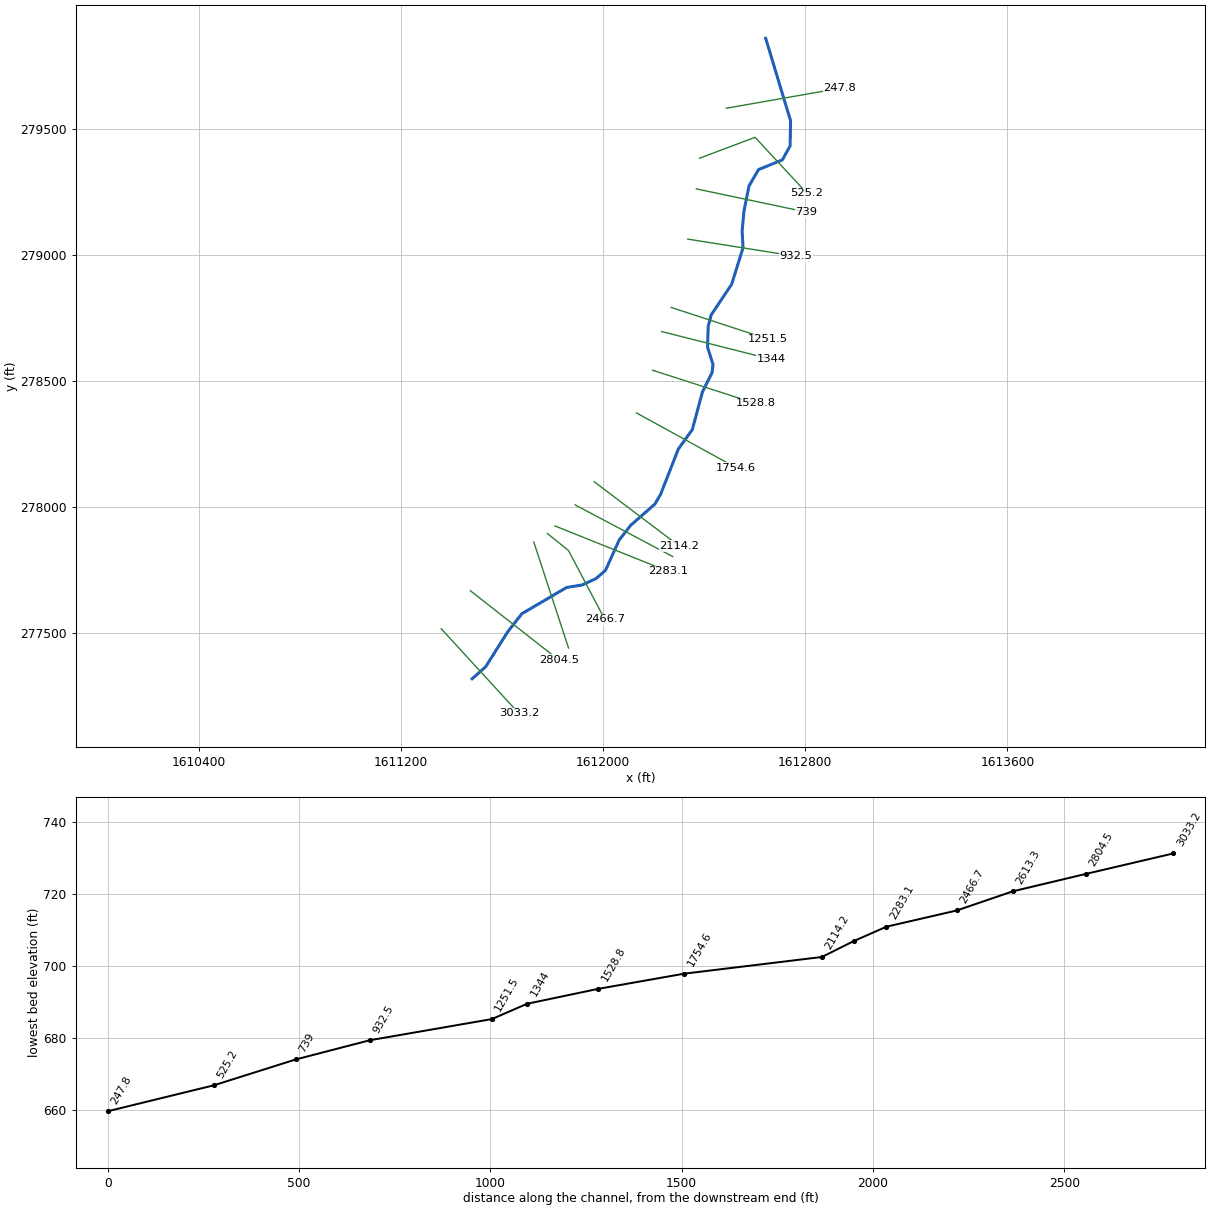
--- cnlybrnch.prj (project) ---

Proj Title=cnlybrnch
Current Plan=p01
Default Exp/Contr=0,0
English Units
Geom File=g01
Flow File=f01
Plan File=p01
BEGIN DESCRIPTION:
END DESCRIPTION:
DSS Export Rating Curves= 0
DSS Export Rating Curve Sorted= 0
DSS Export Volume Flow Curves= 0
DXF OffsetX= 0
DXF OffsetY= 0
DXF ScaleX= 0
DXF ScaleY= 0

--- cnlybrnch.p01 (plan) ---

Plan Title=Approximate Study - 100yr
Program Version=4.00
Short Identifier=Floodplain
Geom File=g01
Flow File=f01
Subcritical Flow
K Sum by GR= 0
Std Step Tol= 0.01
Critical Tol= 0.01
Num of Std Step Trials= 20
Max Error Tol= 0.3
Flow Tol Ratio= 0.001
Split Flow NTrial= 30
Split Flow Tol= 0.02
Split Flow Ratio= 0.02
Log Output Level= 0
Friction Slope Method= 1
Unsteady Friction Slope Method= 2
Unsteady Bridges Friction Slope Method= 1
Parabolic Critical Depth
Global Vel Dist= 0 , 0 , 0
Global Log Level= 0
CheckData=True
Encroach Param=-1 ,0,0, 0
Run HTab= 0
Run UNet= 0
Run PostProcess= 0
Run WQNet= 0
UNET Theta= 0
UNET Theta Warmup= 0
UNET ZTol= 0
UNET ZSATol= 0
UNET MxIter= 0
UNET MaxInSteps= 0
UNET DtIC= 0
UNET DtMin= 0
UNET MaxCRTS= 0
UNET WFStab= 0
UNET SFStab= 0
UNET WFX= 1
UNET SFX= 1
UNET DSS MLevel= 1
UNET DZMax Abort= 0
UNET Convert EG Bridges= 0
UNET Use Existing IB Tables= 0
UNET Froude Reduction=False
UNET Froude Limit= 0
UNET Froude Power= 0
UNET Time Slicing=0,0, 5
Write IC File= 0
Echo Input=False
Echo Output=False
Write Detailed= 0
Detailed Automatic Start=False, 0
WQ ULTIMATE=-1
WQ Max Comp Step=1HOUR
WQ Output Interval=15MIN
WQ Output Selected Increments= 0
WQ Output face flow=0
WQ Output face velocity=0
WQ Output face area=0
WQ Output face dispersion=0
WQ Output cell volume=0
WQ Output cell surface area=0
WQ Output cell continuity=0
WQ Output face conc=0
WQ Output face dconc_dx=0
WQ Output face courant=0
WQ Output face peclet=0
WQ Output face adv mass=0
WQ Output face disp mass=0
WQ Output cell mass=0
WQ Output cell source sink temp=0
WQ Output cell source sink nsm=0
WQ Output MaxMinRange=-1
WQ Daily Max Min Mean=-1
WQ Daily Range=0
WQ Daily Time=0
WQ Create Restart=0
WQ Fixed Restart=0
WQ System Summary=False
Sorting and Armoring Iterations= 10
XS Update Threshold= 0.02
Hydraulics Update Threshold= 0.02
Energy Slope Method= 1
Volume Change Method= 0
XS Weighting Method= 0
Number of US Weighted Cross Sections= 1
Number of DS Weighted Cross Sections= 1
Upstream XS Weight=0.25
Main XS Weight=0.5
Downstream XS Weight=0.25
Number of DS XS's Weighted with US Boundary= 1
Upstream Boundary Weight= 1
Weight of XSs Associated with US Boundary= 0
Number of US XS's Weighted with DS Boundary= 1
Downstream Boundary Weight= 0.5
Weight of XSs Associated with DS Boundary= 0.5
Sediment Output Level= 4
Mass or Volume Output= 0
Output Increment Type= 1
Profile and TS Output Increment= 10
XS Output Flag= 0
XS Output Increment= 10
Disregard all LS=0
Disregard all Conn=0
Disregard all Breaches=0
Disregard all Pumps=0

--- cnlybrnch.f01 (steady flow) ---

Flow Title=USGS Regression Equation
Program Version=4.00
Number of Profiles= 1
Profile Names=P100yr
River Rch & RM=cnlybrnch,Main            ,3033.2
     283
River Rch & RM=cnlybrnch,Main            ,2804.5
     425
River Rch & RM=cnlybrnch,Main            ,247.8
     472
Boundary for River Rch & Prof#=cnlybrnch,Main            , 1
Up Type= 0
Dn Type= 3
Dn Slope=0.018029
DSS Import GetInterval= 0
DSS Import GetPeak= 0
DSS Import FillOption= 0

--- cnlybrnch.g01 (geometry) ---

Geom Title=USGS 3m DEM
Program Version=4.00

River Reach=cnlybrnch       ,Main
Reach XY= 30
     1611482.041      277320.261     1611535.358      277367.595
     1611622.805      277506.473     1611678.724      277578.191
     1611855.664      277682.241     1611917.304      277692.226
     1611972.999       277718.04      1612009.98      277750.758
      1612063.92      277870.608     1612109.235      277928.611
     1612205.209      278012.984     1612227.724      278051.327
     1612298.218      278231.639      1612353.33      278308.437
      1612393.31      278457.532     1612431.909      278535.526
     1612435.141      278567.227     1612413.555      278635.155
     1612416.156      278717.778     1612427.858      278763.164
     1612509.056      278884.729     1612554.067      279029.606
     1612550.409      279097.112     1612558.118      279177.592
      1612577.68      279274.764     1612615.718      279339.823
     1612709.371      279377.589     1612740.352      279433.218
     1612742.066      279533.069     1612643.689      279859.904

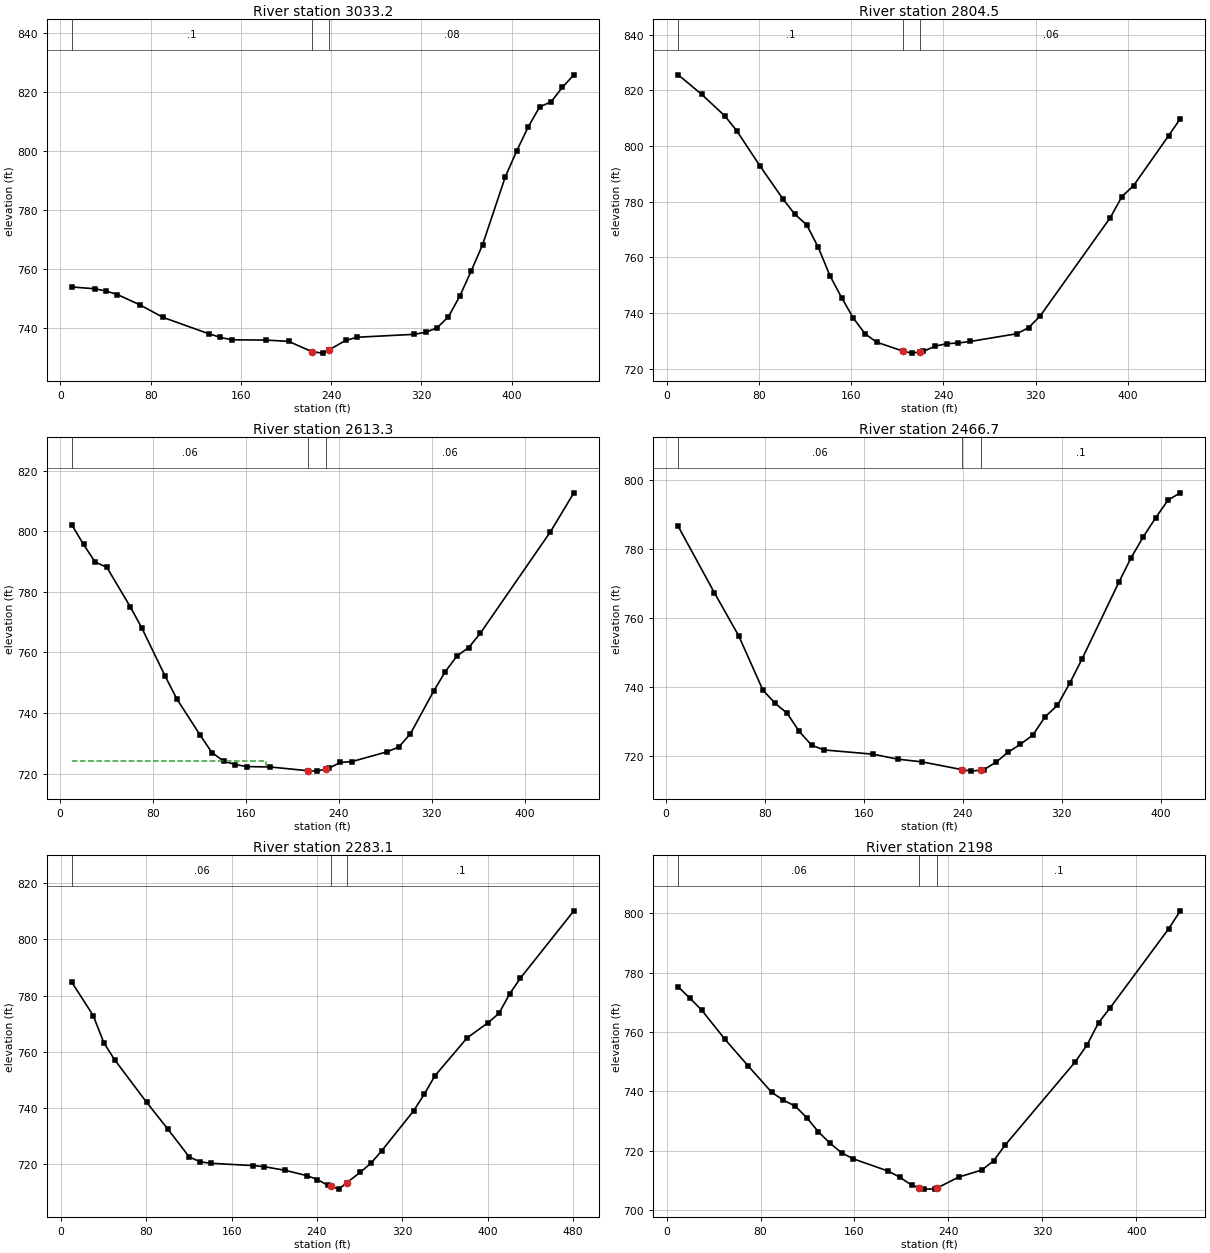
Type RM Length L Ch R = 1 ,3033.2  ,224.9,228.7,232.4
XS GIS Cut Line= 2
     1611359.745      277518.756     1611666.898      277183.074
#Sta/Elev= 30
    10.1   753.8    30.3  753.19    40.4  752.44    50.6  751.22    70.8  747.67
      91  743.47   131.4  737.93   141.6  736.71   151.7  735.86     182  735.77
   202.2  735.34   223.1 731.796   232.6  731.34   238.1 732.433   252.8  735.67
   262.9  736.73   313.4  737.72   323.6  738.41   333.7   739.9   343.8  743.64
   353.9  750.66     364  759.18   374.1  768.12   394.3  791.23   404.4  800.01
   414.6  808.14   424.7  814.93   434.8  816.63   444.9  821.57     455  825.81
#Mann= 3 , 0 , 0
    10.1      .1       0   223.1    .045       0   238.1     .08       0
Bank Sta=223.1,238.1
XS Rating Curve= 0 ,0
Exp/Cntr=0.3,0.1

Type RM Length L Ch R = 1 ,2804.5  ,204.6,191.2,177.9
XS GIS Cut Line= 2
     1611475.058      277669.355     1611825.633      277394.472
#Sta/Elev= 30
    10.1  825.58    30.4  818.58    50.6  810.78    60.7  805.57      81  792.85
   101.2  780.83   111.4  775.45   121.5  771.72   131.6  763.58   141.7  753.42
   151.9  745.49     162  738.19   172.1   732.6   182.2  729.57   205.1  726.36
   212.6  725.65   220.1  726.13   222.7   726.3   232.9  728.15     243  729.05
   253.1  729.29   263.2  729.83   303.7  732.61   313.9  734.78     324  739.01
   384.7  774.25   394.9  781.86     405  785.83   435.4  803.73   445.5  809.84
#Mann= 3 , 0 , 0
    10.1      .1       0   205.1    .045       0   220.1     .06       0
Bank Sta=205.1,220.1
XS Rating Curve= 0 ,0
Exp/Cntr=0.3,0.1

Type RM Length L Ch R = 1 ,2613.3  ,142.8,146.6,150.4
XS GIS Cut Line= 2
     1611726.038       277862.57     1611863.479      277442.278
#Sta/Elev= 30
      10  802.18    20.1  795.69    30.1  789.88    40.2  788.11    60.3  775.12
    70.3  768.09    90.4  752.17   100.5  744.62   120.6  732.65   130.6  726.96
   140.7  724.12   150.7  722.98   160.8  722.31   180.9  722.18   213.6  720.93
   221.1  720.81   228.6  721.52   231.1  721.76   241.2  723.67   251.2  723.97
   281.4  727.19   291.4  728.74   301.5  733.13   321.6   747.3   331.6  753.69
   341.7   758.9   351.7  761.61   361.8   766.4   422.1  799.88   442.2  812.72
#Mann= 3 , 0 , 0
      10     .06       0   213.6    .045       0   228.6     .06       0
#XS Ineff= 2 , 0
       0   176.8     724               0
Permanent Ineff=
       F       F
Bank Sta=213.6,228.6
XS Rating Curve= 0 ,0
Exp/Cntr=0.3,0.1

Type RM Length L Ch R = 1 ,2466.7  ,167.6,183.6,199.6
XS GIS Cut Line= 3
     1611779.819      277896.432     1611863.479      277828.708
     1612006.897      277555.816
#Sta/Elev= 30
     9.8  786.53    39.1  767.24    58.7  754.77    78.3  738.99    88.1  735.22
    97.9  732.28   107.6  727.04   117.6  723.05   127.5  721.65   167.3  720.41
   187.2  718.97   207.1  718.17   239.4  715.92   246.9  715.49   254.4  715.78
   256.8  715.87   266.8  718.06   276.7  721.01   286.6  723.29   296.6  725.95
   306.5  731.24   316.5   734.6   326.4  740.97   336.4  748.03   366.2  770.34
   376.1  777.45   386.1   783.6     396  789.07     406  794.18   415.9  796.29
#Mann= 3 , 0 , 0
     9.8     .06       0   239.4    .045       0   254.4      .1       0
Bank Sta=239.4,254.4
XS Rating Curve= 0 ,0
Exp/Cntr=0.3,0.1

Type RM Length L Ch R = 1 ,2283.1  ,87.5,85.1,82.7
XS GIS Cut Line= 2
     1611809.698      277926.311     1612255.885      277747.039
#Sta/Elev= 30
      10  784.76    30.1  772.87    40.1  763.15    50.1  757.16    80.1  741.99
   100.2  732.34   120.2  722.46   130.2  720.76   140.2  720.21   180.3  719.37
   190.3     719   210.4  717.68   230.4  715.81   240.4  714.41   250.4  712.31
     253  711.97   260.5  710.99     268  713.29   280.5  716.97   290.5  720.21
   300.5  724.57   330.6  738.88   340.6  744.83   350.6  751.38   380.7  764.87
   400.7  770.39   410.7  773.66   420.7   780.6   430.8  786.22   480.9   810.2
#Mann= 3 , 0 , 0
      10     .06       0     253    .045       0     268      .1       0
Bank Sta=253,268
XS Rating Curve= 0 ,0
Exp/Cntr=0.3,0.1

Type RM Length L Ch R = 1 ,2198    ,87.4,83.8,80.2
XS GIS Cut Line= 2
     1611889.374      278009.971     1612275.804      277804.805
#Sta/Elev= 30
     9.9  775.14    19.9  771.34    29.8  767.37    49.7  757.49    69.6  748.46
    89.5  739.64    99.4     737   109.4  735.02   119.3  731.12   129.3   726.3
   139.2  722.48   149.2   719.2   159.1   717.2   188.9  713.06   198.9  710.95
   208.8  708.31   215.3 707.463   218.8  707.01   228.7  707.07   230.3 707.374
   248.6  711.04   268.5  713.46   278.4  716.52   288.4  721.89     348  749.89
     358  755.56   367.9  763.11   377.9  768.19   427.6  794.74   437.5  800.79
#Mann= 3 , 0 , 0
     9.9     .06       0   215.3    .045       0   230.3      .1       0
Bank Sta=215.3,230.3
XS Rating Curve= 0 ,0
Exp/Cntr=0.3,0.1

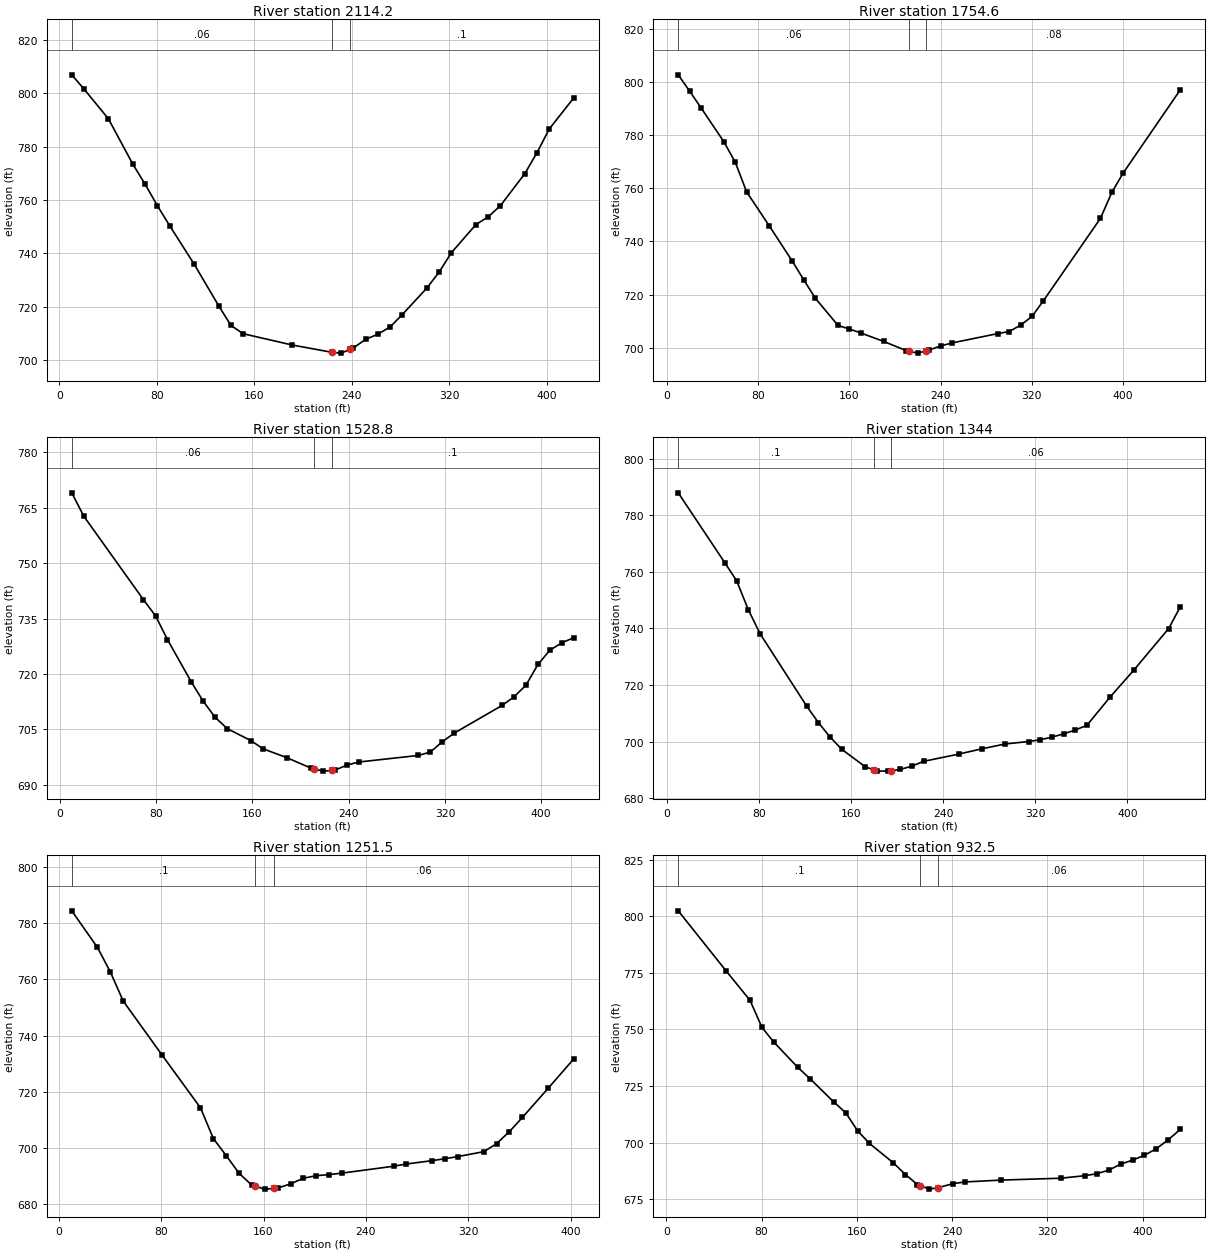
Type RM Length L Ch R = 1 ,2114.2  ,356.4,359.6,362.9
XS GIS Cut Line= 2
     1611965.067      278101.599     1612301.699      277846.635
#Sta/Elev= 30
    10.1  806.93    20.1  801.64    40.2  790.42    60.3  773.37    70.4  765.86
    80.4  757.84    90.5  750.35   110.6  735.92   130.7  720.34   140.8  712.96
   150.8  709.86     191  705.63   223.8  702.88   231.3  702.58   238.8  704.05
   241.3  704.55   251.4  707.74   261.4  709.69   271.5   712.4   281.5  717.06
   301.6  726.96   311.7  732.97   321.7   740.2   341.9  750.78   351.9  753.66
     362  757.85   382.1  769.92   392.1  777.78   402.2  786.69   422.3  798.32
#Mann= 3 , 0 , 0
    10.1     .06       0   223.8    .045       0   238.8      .1       0
Bank Sta=223.8,238.8
XS Rating Curve= 0 ,0
Exp/Cntr=0.3,0.1

Type RM Length L Ch R = 1 ,1754.6  ,221.5,225.9,230.2
XS GIS Cut Line= 2
     1612132.387       278374.49     1612526.784      278157.372
#Sta/Elev= 30
      10  802.75      20   796.6      30  790.32      50  777.56      60  769.82
      70  758.64      90  745.76   110.1  732.52   120.1  725.52   130.1  718.68
   150.1  708.37   160.1  707.03   170.1  705.54   190.1  702.36   210.1  698.86
   212.6  698.63   220.1  697.95   227.6  698.83   230.1  699.12   240.1  700.66
   250.1  701.79   290.1   705.3   300.1  706.08   310.1  708.45   320.1  711.75
   330.2  717.68   380.2  748.72   390.2  758.52   400.2  765.83   450.2  797.12
#Mann= 3 , 0 , 0
      10     .06       0   212.6    .045       0   227.6     .08       0
Bank Sta=212.6,227.6
XS Rating Curve= 0 ,0
Exp/Cntr=0.3,0.1

Type RM Length L Ch R = 1 ,1528.8  ,183.5,184.8,186.1
XS GIS Cut Line= 2
     1612196.128      278543.802     1612602.477      278412.336
#Sta/Elev= 30
     9.9  769.02    19.9  762.69    69.5  740.08    79.5  735.75    89.4  729.31
   109.3   717.8   119.2  712.59   129.1  708.24   139.1  705.21   158.9  701.94
   168.8  699.76   188.7  697.34   208.6  694.54     211  694.34   218.5  693.71
     226  693.89   228.4  693.94   238.4  695.33   248.3  696.17     298  697.96
   307.9  698.88   317.8  701.65   327.8  704.02   367.5  711.49   377.4  713.81
   387.4     717   397.3   722.6   407.2  726.43   417.2  728.46   427.1  729.82
#Mann= 3 , 0 , 0
     9.9     .06       0     211    .045       0     226      .1       0
Bank Sta=211,226
XS Rating Curve= 0 ,0
Exp/Cntr=0.3,0.1

Type RM Length L Ch R = 1 ,1344    ,93.9,92.4,91
XS GIS Cut Line= 2
     1612231.982      278697.179     1612664.226      278587.624
#Sta/Elev= 30
    10.1  787.95    50.7  763.14    60.8  756.87    70.9  746.66    81.1  738.17
   121.6  712.56   131.7  706.77   141.9  701.64     152  697.32   172.3  691.16
   180.1 689.971   182.4  689.62   192.6  689.59   195.1 689.737   202.7  690.18
   212.8  691.33     223  693.04   253.4   695.6   273.6  697.47   293.9  699.19
   314.2  700.05   324.3  700.68   334.4  701.58   344.6  702.77   354.7  704.11
   364.8  705.78   385.1  715.84   405.4  725.23   435.8  739.98   445.9  747.68
#Mann= 3 , 0 , 0
    10.1      .1       0   180.1    .045       0   195.1     .06       0
Bank Sta=180.1,195.1
XS Rating Curve= 0 ,0
Exp/Cntr=0.3,0.1

Type RM Length L Ch R = 1 ,1251.5  ,315.5,319,322.5
XS GIS Cut Line= 2
     1612269.828       278792.79     1612652.274        278667.3
#Sta/Elev= 30
    10.1  784.38    30.2  771.33    40.3  762.57    50.3  752.27    80.5  733.15
   110.7  714.27   120.8  703.29   130.8  697.27   140.9  690.95   150.9   686.7
   153.5  686.35     161  685.33   168.5  685.59   171.1  685.68   181.1  687.22
   191.2   689.2   201.3  690.14   211.3  690.49   221.4  691.04   261.6  693.47
   271.7  694.28   291.8  695.47   301.9  696.17   311.9  696.92   332.1  698.66
   342.1   701.5   352.2  705.84   362.3  710.84   382.4  721.21   402.5   731.7
#Mann= 3 , 0 , 0
    10.1      .1       0   153.5    .045       0   168.5     .06       0
Bank Sta=153.5,168.5
XS Rating Curve= 0 ,0
Exp/Cntr=0.3,0.1

Type RM Length L Ch R = 1 ,932.5   ,194.7,193.6,192.5
XS GIS Cut Line= 2
     1612335.561       279063.69     1612761.829      278995.965
#Sta/Elev= 30
      10  802.41    50.2  775.86    70.3  762.85    80.3   750.9    90.3  744.39
   110.4  733.25   120.5  728.31   140.5  718.02   150.6  713.23   160.6  705.25
   170.6  699.63   190.7  691.04   200.8  685.91   210.8   681.5   213.3  680.99
   220.8  679.46   228.3  680.12   240.9  681.91   250.9  682.64   281.1  683.45
   331.2  684.28   351.3  685.39   361.4  686.26   371.4  687.83   381.4  690.46
   391.5  692.28   401.5  694.41   411.5  697.35   421.6   701.3   431.6  705.89
#Mann= 3 , 0 , 0
      10      .1       0   213.3    .045       0   228.3     .06       0
Bank Sta=213.3,228.3
XS Rating Curve= 0 ,0
Exp/Cntr=0.3,0.1

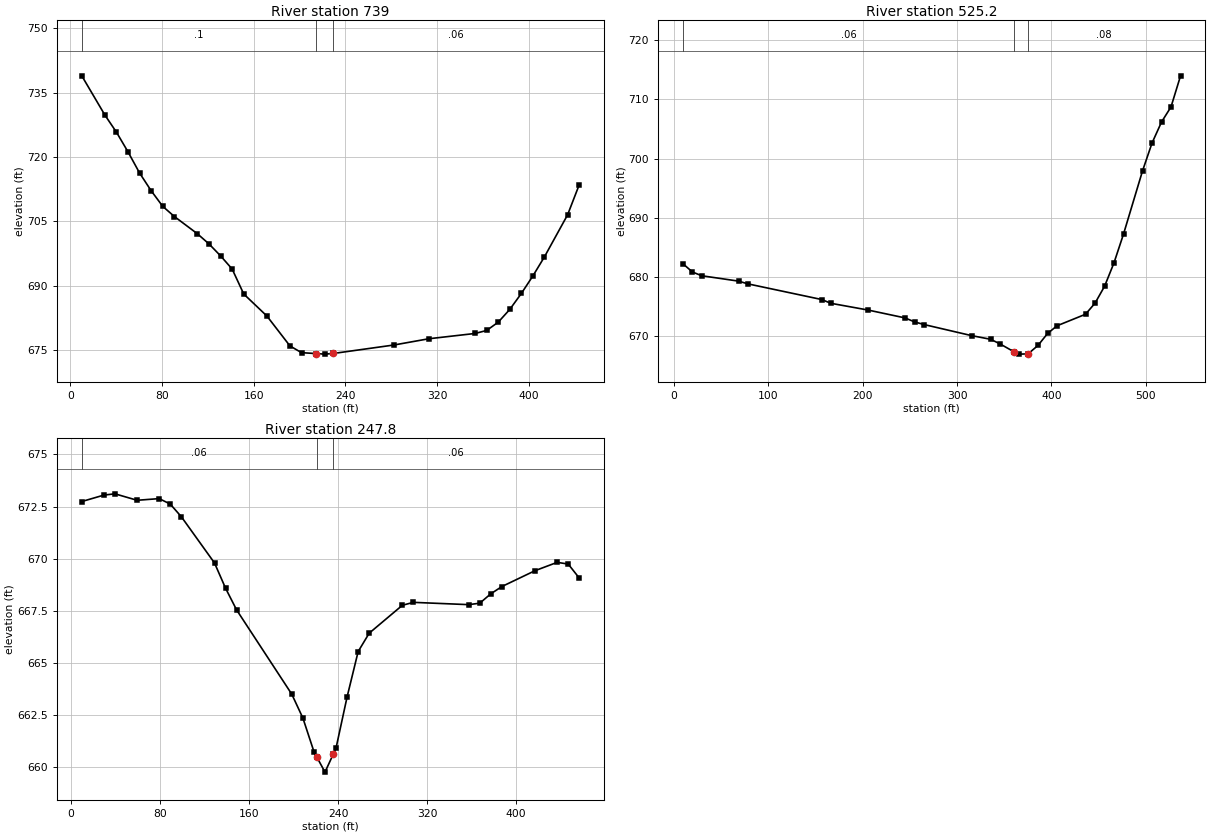
Type RM Length L Ch R = 1 ,739     ,227.3,213.8,199.9
XS GIS Cut Line= 2
     1612369.424       279262.88     1612803.659      279171.253
#Sta/Elev= 30
    10.1  738.91    30.3  729.75    40.3   725.8    50.4  721.21    60.5  716.28
    70.6  712.15    80.7  708.52    90.8  706.16   110.9  702.14     121  699.78
   131.1     697   141.2  693.93   151.3  688.12   171.5  682.99   191.6  676.03
   201.7  674.46   214.4  674.25   221.9  674.12   229.4  674.27   282.4  676.25
   312.7   677.7     353  678.93   363.1  679.63   373.2  681.56   383.3  684.54
   393.4  688.26   403.5  692.36   413.5  696.77   433.7  706.56   443.8  713.54
#Mann= 3 , 0 , 0
    10.1      .1       0   214.4    .045       0   229.4     .06       0
Bank Sta=214.4,229.4
XS Rating Curve= 0 ,0
Exp/Cntr=0.3,0.1

Type RM Length L Ch R = 1 ,525.2   ,255.1,277.3,299.9
XS GIS Cut Line= 3
     1612381.796      279384.531     1612601.622      279467.357
     1612806.848      279245.805
#Sta/Elev= 30
     9.8   682.2    19.6  680.84    29.4   680.2    68.5  679.29    78.3  678.83
   156.6  676.18   166.4  675.54   205.5  674.41     245  673.07     255   672.4
   265.1  671.95   315.4  670.08   335.6  669.46   345.6  668.68   360.3 667.353
   365.8  666.95   375.3 666.988   385.9  668.43     396  670.44     406  671.74
   436.2  673.69   446.3  675.57   456.4  678.42   466.4  682.39   476.5  687.26
   496.6  697.92   506.7  702.64   516.8   706.2   526.8  708.74   536.9  713.99
#Mann= 3 , 0 , 0
     9.8     .06       0   360.3    .045       0   375.3     .08       0
Bank Sta=360.3,375.3
XS Rating Curve= 0 ,0
Exp/Cntr=0.3,0.1

Type RM Length L Ch R = 1 ,247.8   ,246.1,247.8,249.6
XS GIS Cut Line= 2
       1612487.9      279582.724     1612937.651      279661.738
#Sta/Elev= 30
     9.9  672.74    29.8  673.05    39.7  673.11    59.6   672.8    79.4  672.88
    89.3  672.62    99.3  672.01   129.1  669.79     139  668.58   148.9  667.54
   198.5  663.49   208.5  662.34   218.4  660.73   220.8  660.49   228.3  659.75
   235.8  660.62   238.2   660.9   248.2  663.37   258.1  665.54     268  666.42
   297.8  667.76   307.7   667.9   357.4  667.79   367.3  667.86   377.2  668.31
   387.2  668.66   416.9  669.42   436.8  669.82   446.7  669.74   456.6  669.07
#Mann= 3 , 0 , 0
     9.9     .06       0   220.8    .045       0   235.8     .06       0
Bank Sta=220.8,235.8
XS Rating Curve= 0 ,0
Exp/Cntr=0.3,0.1

Chan Stop Cuts=-1
Use User Specified Reach Order=0